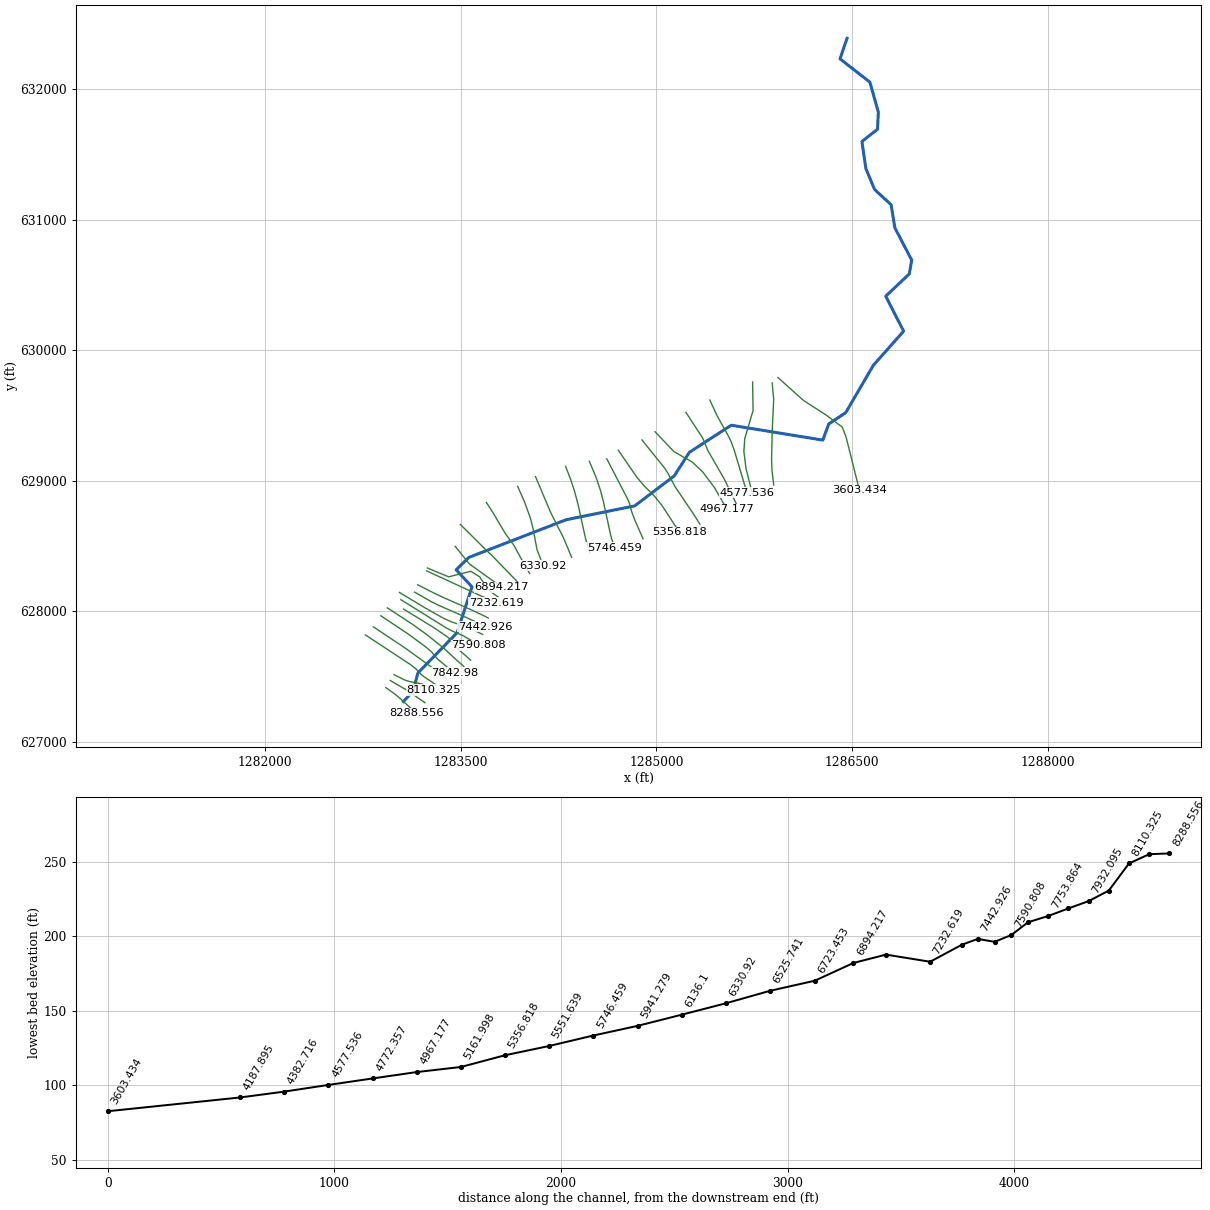
--- 770_ras.prj (project) ---

Proj Title=770
Current Plan=p01
Default Exp/Contr=0.3,0.1
English Units
Geom File=g01
Flow File=f01
Plan File=p01
Y Axis Title=Elevation
X Axis Title(PF)=Main Channel Distance
X Axis Title(XS)=Station
BEGIN DESCRIPTION:
RFD model 770 exported to HEC-RAS
END DESCRIPTION:

--- 770_ras.p01 (plan) ---

Plan Title=Plan 01
Program Version=4.10
Short Identifier=Plan 01
Geom File=g01
Flow File=f01
Subcritical Flow
Calc Critical at every XS
Secant Critical Depth

--- 770_ras.f01 (steady flow) ---

Flow Title=Flow 01
Program Version=5.01
Number of Profiles= 5
Profile Names=10yr,25yr,50yr,100yr,500yr
River Rch & RM=770,44,8288.556
  437.69  532.24   637.3  693.08  833.22
River Rch & RM=770,44,8199.441
  441.29  537.25  643.47  700.64  843.62
River Rch & RM=770,44,8110.325
  446.24  544.17     652  711.11  858.03
River Rch & RM=770,44, 8021.21
  447.64  546.13  654.41  714.07  862.12
River Rch & RM=770,44, 7842.98
  451.11  550.99   660.4  721.43  872.28
River Rch & RM=770,44,7753.864
  454.55   555.8  666.33  728.72  882.37
River Rch & RM=770,44,7664.749
   527.8  659.62  794.74  888.58 1106.86
River Rch & RM=770,44,7590.808
  531.04  664.27   800.5  895.82 1117.19
River Rch & RM=770,44,7442.926
  537.44  673.44  811.87  910.16 1137.65
River Rch & RM=770,44,7372.307
  600.75  765.12  925.81 1055.14 1347.02
River Rch & RM=770,44,7232.619
  613.01  783.05  948.15 1083.83 1388.97
River Rch & RM=770,44,7037.954
  637.29   818.7  992.59 1141.17 1473.27
River Rch & RM=770,44,6894.217
  638.51  820.49  994.83 1144.07 1477.54
River Rch & RM=770,44,6723.453
  641.74  825.25 1000.76 1151.75 1488.89
River Rch & RM=770,44,6525.741
  644.15   828.8 1005.19 1157.49 1497.37
River Rch & RM=770,44, 6330.92
  671.63  869.46 1055.96 1223.49 1595.35
River Rch & RM=770,44,  6136.1
  682.37  885.42 1075.91 1249.54 1634.22
River Rch & RM=770,44,5941.279
  693.22  901.57 1096.11 1275.97  1673.8
River Rch & RM=770,44,5746.459
  697.14   907.4 1103.42 1285.54 1688.15
River Rch & RM=770,44,5551.639
  704.86  918.94 1117.85 1304.49 1716.62
River Rch & RM=770,44,5356.818
  725.97  950.55 1157.43 1356.58 1795.19
River Rch & RM=770,44,5161.998
  838.69 1121.55 1372.21 1643.01 2234.59
River Rch & RM=770,44,4967.177
  851.61 1141.37 1397.17 1676.69 2287.02
River Rch & RM=770,44,4772.357
   855.5 1147.36 1404.71 1686.88 2302.91
River Rch & RM=770,44,4577.536
  866.78  1164.7 1426.57 1716.45  2349.1
River Rch & RM=770,44,4382.716
  869.81 1169.38 1432.46 1724.43 2361.59
River Rch & RM=770,44,4187.895
  872.08 1172.87 1436.87  1730.4 2370.93
River Rch & RM=770,44,3603.434
 1016.16 1397.53  1720.8 2119.75 2989.89
River Rch & RM=770,44,3476.221
 1017.95 1400.35 1724.37 2124.69 2997.87
River Rch & RM=770,44,3117.379
 1022.69 1407.83 1733.85 2137.84 3019.07
River Rch & RM=770,44,2758.538
  1034.4 1426.32 1757.28 2170.39 3071.66
River Rch & RM=770,44,2490.719
 1035.17 1427.54 1758.83 2172.54 3075.15
River Rch & RM=770,44,2272.784
 1117.94 1559.12 1925.86 2406.08 3455.78
River Rch & RM=770,44,2038.368
 1118.46 1559.95  1926.9 2407.55  3458.2
River Rch & RM=770,44,1860.541
 1121.88 1565.42 1933.86 2417.34 3474.27
River Rch & RM=770,44,1682.714
 1135.59 1587.36 1961.76 2456.62 3538.87
River Rch & RM=770,44,1504.887
 1137.43 1590.31 1965.51 2461.91 3547.58
River Rch & RM=770,44, 1327.06
 1138.77 1592.46 1968.24 2465.75 3553.91
River Rch & RM=770,44,821.1134
 1145.75 1603.65 1982.47 2485.83    3587
River Rch & RM=770,44,644.7654
 1147.73 1606.83 1986.51 2491.53 3596.42
River Rch & RM=770,44,422.9943
 1149.71    1610 1990.55 2497.23 3605.82
River Rch & RM=770,44,  85.839
 1152.17 1613.95 1995.58 2504.34 3617.55
Boundary for River Rch & Prof#=770,44,1
Up Type= 0
Dn Type= 2
Boundary for River Rch & Prof#=770,44,2
Up Type= 0
Dn Type= 2
Boundary for River Rch & Prof#=770,44,2
Up Type= 0
Dn Type= 2
Boundary for River Rch & Prof#=770,44,2
Up Type= 0
Dn Type= 2
Boundary for River Rch & Prof#=770,44,2
Up Type= 0
Dn Type= 2

--- 770_ras.g01 (geometry) ---

Geom Title=770
Program Version=4.10

River Reach=770,44
Reach XY= 30
1283060.52526471627309.0375881641283136.32080856627391.222521663
1283171.32080218627527.889146745 1283472.1540558627837.055712774
1283586.32069919628188.7222717111283464.61105406628318.471629545
1283560.96522069628413.5237128881284307.98716804628702.888764516
1284832.98701629628808.7220510241285136.32026684629038.721973807
1285252.15357134629219.5552500341285572.98681608 629427.05517903
1286274.65327236629312.8885256051286320.48659584  629437.0551541
1286450.48655999629523.721791208 1286662.9865081629887.888343528
1286894.03390375 630147.755803541286756.97216514630415.824060097
1286937.09369293630586.1799628881286956.31977847630692.054762796
 1286827.1531572630939.5546931621286797.98650444631117.054641306
1286671.31987852631233.7212770581286604.65323627 631394.55456461
1286574.65325117631601.2211707981286693.81988543631695.387806043
  1286700.486554631826.2211003451286635.48658001632056.221033916
1286406.31998619632235.3876541411286460.48664153632392.054272741

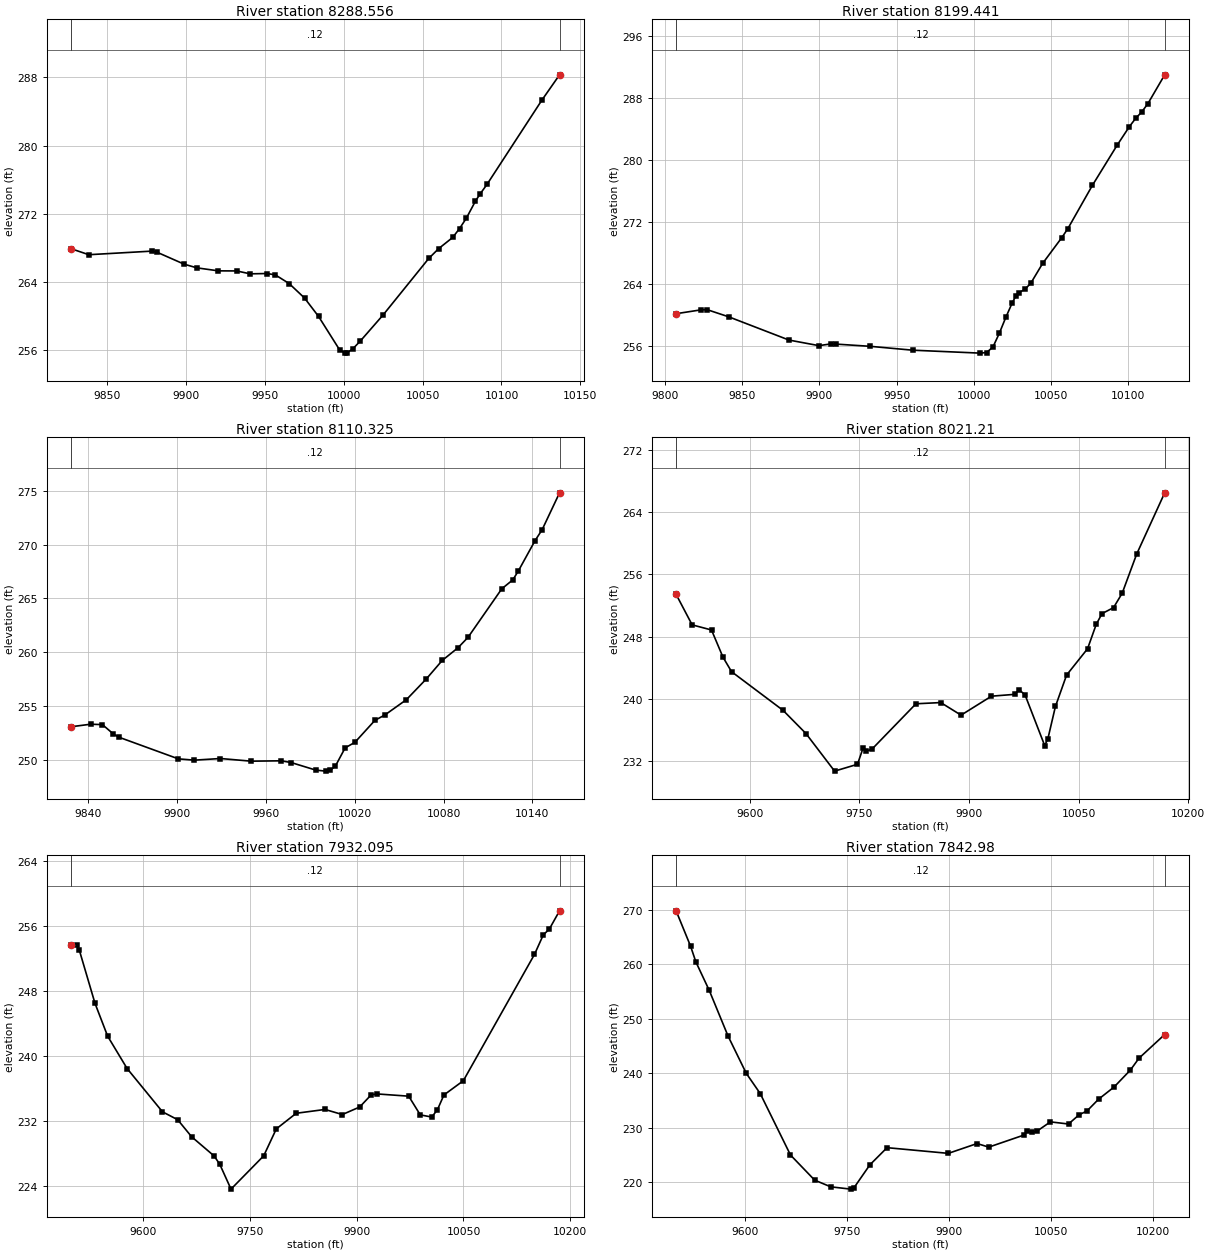
Type RM Length L Ch R = 1 ,8288.556,89.115300,89.115300,89.115300
XS GIS Cut Line= 6
1282925.48737775627416.1444535881282994.60821879627367.018695086
1283035.78345275627333.0657006351283109.69447312627264.668942809
 1283155.2660664627225.0815920831283163.17950296627218.645061702
#Sta/Elev= 30
 9827.34267.90389838.647267.19839878.897267.6214 9881.88 267.4869899.022266.0871
9907.073265.65679920.684265.30549932.301265.29459940.806264.95599951.626264.9916
9956.783264.82929965.509263.81889975.253262.12159984.149259.96039997.493256.0376
10000.98255.658810001.98255.6666 10005.8256.154710010.62257.081510025.07260.1439
10053.98266.769210060.22 267.91310069.09269.219510073.44270.263210077.78271.4889
10083.52273.483410086.47 274.32410090.82275.439910125.59 285.32110136.78288.2877
#Mann= 3 , 0 , 0
 9827.34    0.12       0 9827.34    0.12       010136.78    0.12       0
#XS Ineff= 2 , 0
       09954.559           10064       0
Bank Sta=9827.34,10136.78
Exp/Cntr=0.3,0.1

Type RM Length L Ch R = 1 ,8199.441,89.115300,89.115300,89.115300
XS GIS Cut Line= 6
 1282960.1355504 627471.048481041282989.20522907627453.348594561
1283110.76459545627382.831264839 1283124.4760958627372.477221176
1283147.07993352 627354.671997861283225.79096699627300.277730033
#Sta/Elev= 30
9807.252260.1947 9823.57260.69849827.411260.71099841.286259.79469880.321256.7966
9899.651256.07799907.236256.29399911.029256.27199932.628255.99359960.337255.4916
10004.06255.1125 10008.2255.191510012.34255.909110016.47257.685610020.62259.7094
10024.77261.582610027.23262.509310028.86262.889310032.95263.327810036.84264.1327
 10044.5266.684110056.78 269.97510060.77271.148310076.72 276.75310092.67281.9078
10100.65284.320610104.64285.366910108.63286.207810112.61287.278110123.48290.9897
#Mann= 3 , 0 , 0
9807.252    0.12       09807.252    0.12       010123.48    0.12       0
#XS Ineff= 2 , 0
       09943.822        10039.21       0
Bank Sta=9807.252,10123.48
Exp/Cntr=0.3,0.1

Type RM Length L Ch R = 1 ,8110.325,89.115300,89.115300,89.115300
XS GIS Cut Line= 6
1282988.20583297 627515.529082671283071.10644475627474.562170625
1283102.99318159627463.8420897571283201.19088495627444.833560482
 1283239.4190028 627428.438422621283293.20179337627397.980039239
#Sta/Elev= 30
9828.447253.05789841.724253.29459849.672253.25889857.129252.38039860.858252.0845
9900.914250.07349911.709249.95099929.368250.10499950.136 249.8569970.421249.8909
9977.139 249.728 9993.74249.026610000.33248.931110003.63249.030610006.94249.3926
10013.55 251.09310020.16251.612210033.67253.655710040.49254.164210054.89255.5749
10068.37257.508810079.08259.223110089.79260.412610096.49261.371510119.33265.8939
10126.79266.726510130.53267.559510141.79270.376910146.55271.386310158.32274.8188
#Mann= 3 , 0 , 0
9828.447    0.12       09828.447    0.12       010158.32    0.12       0
#XS Ineff= 2 , 0
       09956.589        10038.95       0
Bank Sta=9828.447,10158.32
Exp/Cntr=0.3,0.1

Type RM Length L Ch R = 1 , 8021.21,89.115300,89.115300,89.115300
XS GIS Cut Line= 6
1282769.44169697 627819.762538121283115.13221356627592.484077364
1283158.86275494627557.7837213581283192.16806099627521.114313334
1283212.90752375627503.250533462 1283314.3900041627435.242064923
#Sta/Elev= 30
9499.077253.41129521.018249.49549547.537248.83549563.204245.34839574.955243.4827
 9645.46238.51739676.795235.53719715.965230.7133  9747.3231.59269755.134233.7359
9759.051233.28749766.885 233.5129827.313239.36189861.265239.51629889.026237.9019
9930.634240.33769962.303240.57089968.625241.17639976.731240.472910003.47233.9968
10007.83234.860410018.17 239.01410033.44243.046110062.15 246.429   10074249.5536
10081.89250.938710097.69 251.70710109.54  253.5610129.29258.568110167.71266.4498
#Mann= 3 , 0 , 0
9499.077    0.12       09499.077    0.12       010167.71    0.12       0
#XS Ineff= 2 , 0
       09965.157         10058.8       0
Bank Sta=9499.077,10167.71
Exp/Cntr=0.3,0.1

Type RM Length L Ch R = 1 ,7932.095,89.115300,89.115300,89.115300
XS GIS Cut Line= 6
1282829.71524245627882.2183139181283068.23810393627723.480230659
1283241.08873752627598.2307154831283242.73516309627597.095249519
 1283265.3421644627581.1249849051283389.10048735627485.873447523
#Sta/Elev= 30
9499.026253.6077 9506.91253.60689510.851252.98819532.721246.48619550.486242.4432
9577.847 238.4599627.469  233.149648.784232.17029668.489230.06469700.017227.7076
9707.899226.68759723.662223.63389769.591227.73129787.255231.03969815.212232.9619
9855.628  233.439879.938232.80489904.247233.72889920.454 235.2289928.557235.3398
9973.125235.06199989.331232.762110005.47232.4963 10013.5233.411210022.52235.2092
10049.75236.958410149.66252.495710162.08254.905310170.36255.590810184.85257.8522
#Mann= 3 , 0 , 0
9499.026    0.12       09499.026    0.12       010184.85    0.12       0
#XS Ineff= 2 , 0
       09955.443        10058.69       0
Bank Sta=9499.026,10184.85
Exp/Cntr=0.3,0.1

Type RM Length L Ch R = 1 , 7842.98,89.115300,89.115300,89.115300
XS GIS Cut Line= 6
1282887.54308155627966.6784910111283099.06400436627825.736411542
1283233.40841562627726.6351395551283274.17200339627691.691956192
1283322.91205114627634.4393539881283452.66582566627527.530853629
#Sta/Elev= 30
9499.073269.77789520.262263.32339528.147260.40929547.859255.17629575.456246.8214
9602.222239.98799622.765236.27699667.305225.00249702.806220.40279726.472219.1712
9755.925218.75069760.924219.04389784.131223.21519809.321226.35139899.439225.3084
9941.723227.10829958.902226.452410010.83228.672910015.18229.445310021.76229.1501
10029.94229.388510049.53231.082510076.19230.690510091.66232.3701 10103.4233.0833
10120.41235.240410143.26237.479110167.17240.577810179.92242.764810217.65247.0978
#Mann= 3 , 0 , 0
9499.073    0.12       09499.073    0.12       010217.65    0.12       0
#XS Ineff= 2 , 0
       09968.798        10070.31       0
Bank Sta=9499.073,10217.65
Exp/Cntr=0.3,0.1

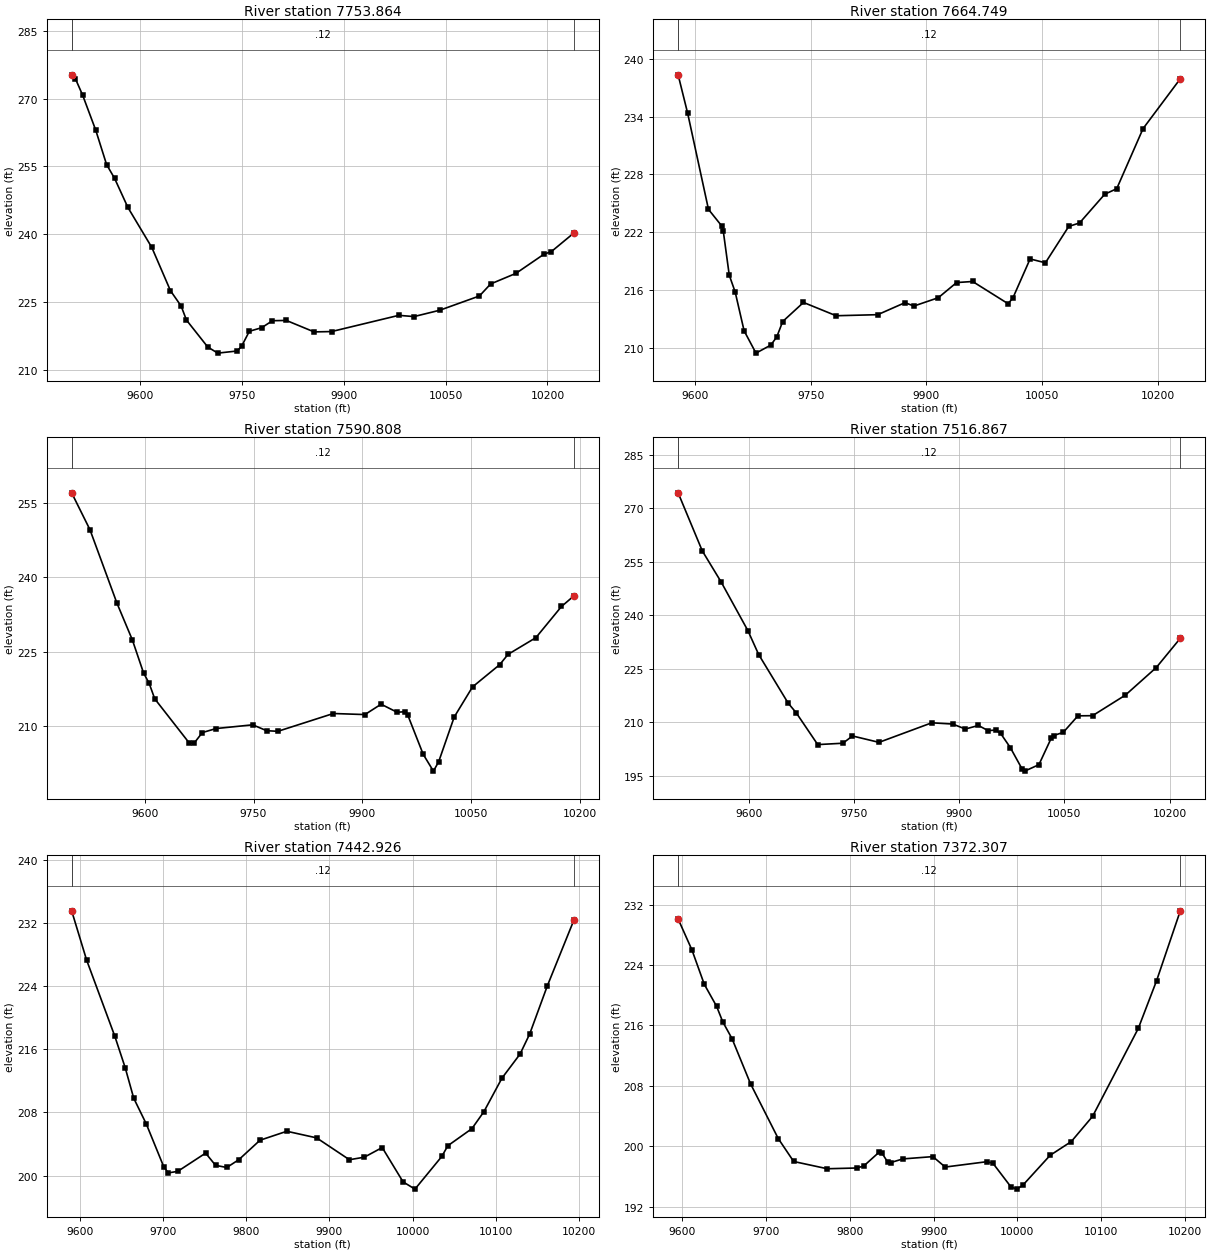
Type RM Length L Ch R = 1 ,7753.864,89.115300,89.115300,89.115300
XS GIS Cut Line= 6
1282937.57553497628027.3614823521283130.44051948627901.100920528
1283236.51956192  627824.71524031283370.30150536627717.977468446
1283466.05319625627628.7503220741283523.92051706627578.717730522
#Sta/Elev= 30
 9499.02275.29269504.589274.41349515.194270.79639534.539263.01349550.486255.4121
 9562.25252.36269581.857245.91639617.149 237.0389644.599227.46269660.284224.0768
9668.127220.96229699.497214.99599714.236213.63639742.892214.11079749.307215.1399
9760.783218.47679778.884219.2645 9794.88220.81949815.307220.87699856.209218.3384
9881.883218.41299980.932222.006410003.37221.734610041.44223.145910099.73226.2986
10116.28228.965310153.55231.308910194.59235.530410205.88236.151410238.82240.2444
#Mann= 3 , 0 , 0
 9499.02    0.12       0 9499.02    0.12       010238.82    0.12       0
#XS Ineff= 2 , 0
       09971.364        10064.19       0
Bank Sta=9499.02,10238.82
Exp/Cntr=0.3,0.1

Type RM Length L Ch R = 1 ,7664.749,73.941100,73.941100,73.941100
XS GIS Cut Line= 6
1283061.92028448628017.9248265771283289.77192295627878.316280276
1283402.59568164627801.4489530181283424.12454444627780.461500227
1283461.44561619627728.1450519711283575.53891477627626.965218738
#Sta/Elev= 30
9578.329238.32959590.735234.32939617.669224.37439635.183222.62199636.908222.0909
9644.603217.54899652.299215.79469663.842211.77979679.233209.46419698.471210.2988
9706.167211.14469713.862212.74339740.796214.72139783.121213.34169836.989213.4516
9872.221214.69389884.031214.35169915.525215.21139939.208216.78349960.008 216.894
10005.93214.589710012.16215.183810034.47219.233310054.31218.833210084.56222.6064
10098.56222.964410131.21225.945810146.73226.517210180.84232.748910229.13237.9216
#Mann= 3 , 0 , 0
9578.329    0.12       09578.329    0.12       010229.13    0.12       0
#XS Ineff= 2 , 0
       09969.001        10057.95       0
Bank Sta=9578.329,10229.13
Exp/Cntr=0.3,0.1

Type RM Length L Ch R = 1 ,7590.808,73.941100,73.941100,73.941100
XS GIS Cut Line= 6
1283040.73541322628090.1376092141283393.98345149627870.749770403
 1283436.0134908627849.0571399031283515.41834569627815.423729822
1283591.47024369627771.3735196291283637.94304696627740.886608481
#Sta/Elev= 30
9499.043257.08279524.315249.62899561.626234.75799582.779227.37699598.227220.7003
9605.951218.59879613.675 215.4649661.123 206.5699667.744206.45299679.331208.6444
9698.434209.46039748.848210.20959768.158209.01869783.607208.89979860.116212.4954
9903.646212.28029925.991214.37429948.144212.7462 9959.22212.86399962.879212.1439
9984.057204.25659998.176200.853710005.38202.7356 10026.9211.795310052.15 217.871
 10089.6222.362910101.11 224.44210139.54227.816510174.86234.115910191.92236.2487
#Mann= 3 , 0 , 0
9499.043    0.12       09499.043    0.12       010191.92    0.12       0
#XS Ineff= 2 , 0
       09953.185        10025.96       0
Bank Sta=9499.043,10191.92
Exp/Cntr=0.3,0.1

Type RM Length L Ch R = 1 ,7516.867,73.941100,73.941100,73.941100
XS GIS Cut Line= 6
 1283029.8340756628145.4851118921283230.29614329628024.850297689
1283372.26752147627945.3362705561283430.19778657  627919.5020037
1283556.71312469627878.5123101171283667.00866264627823.994584724
#Sta/Elev= 30
9499.064274.34449533.541258.06269560.345249.38079598.636235.69499613.952 229.013
9656.072215.3664 9667.56212.66329698.192203.75789734.109204.13989747.786206.1747
9785.605204.38449860.833209.86579890.654209.5194  9908.8208.11829927.404209.1215
9941.131207.67889951.908207.81939959.092206.88679972.898202.9233 9990.03196.8026
  9993.4196.3172 10013.7198.121310031.07205.466510034.55206.283410048.47207.1928
10069.36211.820510090.24211.8623   10137217.620610181.11225.357110215.39233.5637
#Mann= 3 , 0 , 0
9499.064    0.12       09499.064    0.12       010215.39    0.12       0
#XS Ineff= 2 , 0
       09951.292        10056.26       0
Bank Sta=9499.064,10215.39
Exp/Cntr=0.3,0.1

Type RM Length L Ch R = 1 ,7442.926,70.618500,70.618500,70.618500
XS GIS Cut Line= 6
1283145.47063172628148.1331599351283276.24859723628073.381386846
1283342.30044004628041.815131143 1283534.9421483627957.144695967
1283640.77973318627907.882370934 1283688.2206617627884.009021103
#Sta/Elev= 30
9589.849233.53049607.829227.2996 9641.84 217.626 9654.25213.66459664.514 209.797
 9679.63 206.5369700.529201.13799706.083200.33399717.419200.52519751.017202.8387
9762.979201.2896 9776.47201.01879791.015202.0122 9816.43204.47119848.703205.6069
9884.561204.76869924.006202.00079941.935 202.325 9963.45203.54539988.542 199.196
10002.84198.276910035.15202.420510042.38203.772610071.33205.937210085.81208.0945
10107.52212.339310129.23215.379710140.86217.931710162.12224.036310193.97232.3405
#Mann= 3 , 0 , 0
9589.849    0.12       09589.849    0.12       010193.97    0.12       0
#XS Ineff= 2 , 0
       09956.352        10040.87       0
Bank Sta=9589.849,10193.97
Exp/Cntr=0.3,0.1

Type RM Length L Ch R = 1 ,7372.307,139.688500,139.688500,139.688500
XS GIS Cut Line= 6
1283169.34215948628204.5567710251283297.08193058628139.787636861
1283363.13377336628108.2213811431283555.77548164628023.550945982
1283661.61306652627974.2886209491283711.29350916627949.288296878
#Sta/Elev= 30
9595.126230.10089611.613 225.9999626.327 221.4569641.041218.53839648.397216.4821
9659.433214.26289681.504208.2906 9714.61201.03169733.002197.99899773.062197.0378
9808.328197.13839816.626197.40139834.555199.18869838.141199.13959845.313197.9055
9848.753197.85289863.242198.3396  9899.1198.64349913.786197.26329963.645197.9729
9970.817197.75859992.305194.62929999.453194.3406 10006.6 194.87810038.98198.8137
10064.31200.640810089.64203.969410144.22215.616510166.04221.929210194.34231.1755
#Mann= 3 , 0 , 0
9595.126    0.12       09595.126    0.12       010194.34    0.12       0
#XS Ineff= 2 , 0
       09935.872         10058.9       0
Bank Sta=9595.126,10194.34
Exp/Cntr=0.3,0.1

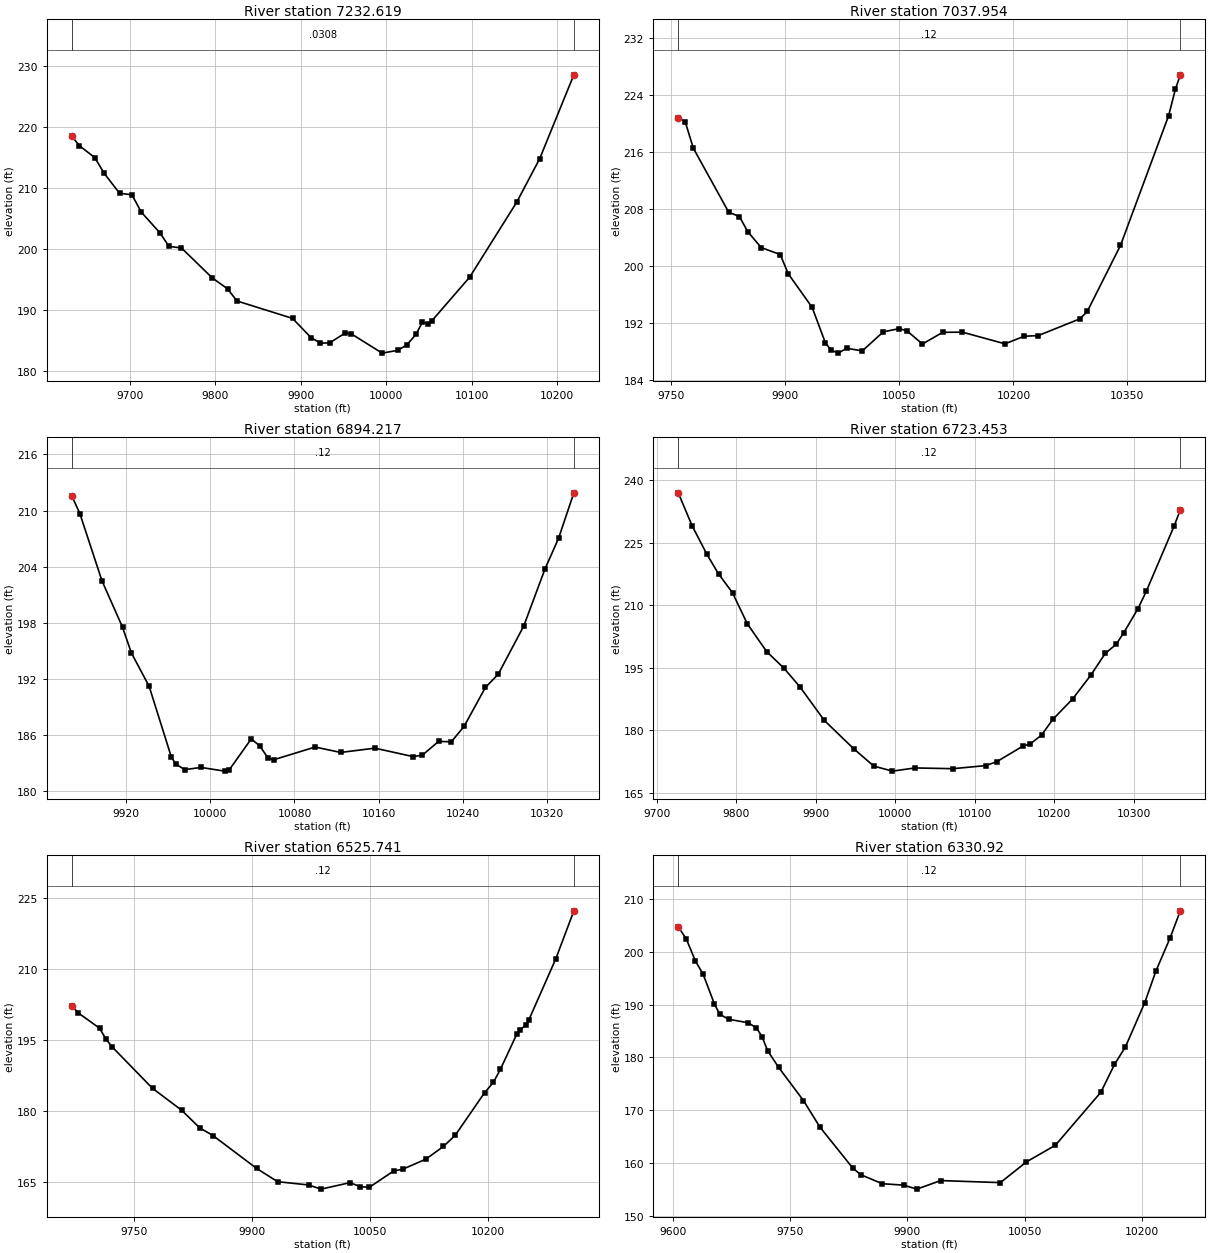
Type RM Length L Ch R = 1 ,7232.619,194.664500,194.664500,194.664500
XS GIS Cut Line= 2
1283238.24406922 628310.929745571283771.57479438628065.206688955
#Sta/Elev= 30
9632.233 218.4359641.194216.87329659.255214.92079670.092212.36899688.154209.0913
9702.603208.8563 9713.44206.02679735.114202.65869745.951200.40519760.513200.1507
9796.523195.25499814.585193.44229825.422 191.4759890.443188.62679912.117185.4753
9922.954184.58179933.791184.61399951.852186.21379959.077186.1079  9995.2182.9421
10013.26183.3937 10024.1184.277710034.94186.032510042.16187.958210049.38187.7436
   10053 188.16610097.65195.375910152.53207.614110179.43214.730810219.45228.4764
#Mann= 3 , 0 , 0
9632.233  0.0308       09632.233  0.0308       010219.45  0.0308       0
#XS Ineff= 2 , 0
       09847.941        10086.35       0
Bank Sta=9632.233,10219.45
Exp/Cntr=0.3,0.1

Type RM Length L Ch R = 1 ,7037.954,143.737600,143.737600,143.737600
XS GIS Cut Line= 6
1283244.55897069628332.7945462021283407.31938741628265.086212873
1283576.66637823628307.7396413981283645.61744922628264.867007658
1283706.78790599628167.0278358461283796.33282688628104.051188216
#Sta/Elev= 30
    9759220.81639768.133220.29519778.853216.55749825.306207.57159839.599206.9308
9850.319204.83659868.186 202.5799893.199 201.6029903.694198.90069935.144194.1747
9952.617  189.189960.216188.14389969.744187.73369980.573188.419410001.11188.0438
10028.77190.725110049.88191.182710060.04190.863110080.28189.015410106.99190.6606
10132.92190.682210188.91189.0415 10214.1190.1072 10232.7190.202610287.66 192.568
10297.23193.610510340.86202.8799 10404.2 221.13410413.05224.835910419.57226.8779
#Mann= 3 , 0 , 0
    9759    0.12       0    9759    0.12       010419.57    0.12       0
#XS Ineff= 2 , 0
       09945.194        10213.47       0
Bank Sta=9759,10419.57
Exp/Cntr=0.3,0.1

Type RM Length L Ch R = 1 ,6894.217,170.763700,170.763700,170.763700
XS GIS Cut Line= 3
1283458.10063741628498.1591295451283566.17355403628364.044546202
1283813.22797668 628186.48026678
#Sta/Elev= 30
 9868.66211.56649876.337209.68029897.252202.50889916.816197.52399925.243194.7729
9942.097191.19749963.165183.63759967.378182.89449975.805182.2941 9991.37182.5278
10013.73182.133210017.94182.245210039.01185.579910047.07184.829610055.24183.4838
10060.86183.3701 10099.6184.709110123.84184.132710156.43184.588410192.52183.6882
 10201.4183.839510216.76185.312410228.89185.271210241.01186.922910261.21191.0834
10273.33192.489910297.57197.644710317.77203.756110330.69207.048710345.14211.8953
#Mann= 3 , 0 , 0
 9868.66    0.12       0 9868.66    0.12       010345.14    0.12       0
#XS Ineff= 2 , 0
       0                10175.39       0
Bank Sta=9868.66,10345.14
Exp/Cntr=0.3,0.1

Type RM Length L Ch R = 1 ,6723.453,197.712200,197.712200,197.712200
XS GIS Cut Line= 6
1283496.46388206628666.9990256281283682.51439628628482.183558673
1283720.03656989628446.3779237571283721.57735851628445.102788284
1283735.38658014628432.2017921211283942.13422668628219.032350093
#Sta/Elev= 30
9726.696236.93739744.154229.03869762.652 222.2449777.401 217.5029795.023212.9789
9813.521205.5755 9837.92198.89269859.765194.88739879.818190.43119910.633182.3539
9947.629175.56499972.924171.40799996.352170.210510024.87170.975410072.33170.7949
10113.46171.530610127.45172.453910160.43176.199210169.86176.7451   10184178.8541
10198.13182.609810223.15 187.51610246.01193.219710264.11198.4161   10278200.6428
10287.67203.444810305.42209.179710315.94213.383210351.13229.094310358.66232.8709
#Mann= 3 , 0 , 0
9726.696    0.12       09726.696    0.12       010358.66    0.12       0
#XS Ineff= 2 , 0
       0                 10147.7       0
Bank Sta=9726.696,10358.66
Exp/Cntr=0.3,0.1

Type RM Length L Ch R = 1 ,6525.741,194.820400,194.820400,194.820400
XS GIS Cut Line= 6
1283696.45490283628835.1345778851283745.49721804628758.770378783
 1283840.3168481628599.328353286 1283909.7442753628502.690662846
1283991.45534405628351.9911574421284028.70040742628290.159340695
#Sta/Elev= 30
 9670.84202.21579679.182200.69829706.162197.48219714.274195.19739722.073193.5469
9773.596184.74929810.698180.11669833.601176.3948 9850.62174.75329906.127167.7974
9932.847164.99469972.133164.30999988.113163.424710025.02164.799310037.83163.9333
 10049.6163.821310080.42167.2521 10092.4 167.65910121.47169.767210143.86172.4604
10158.79174.807810196.11183.805110207.31185.9975 10216.3188.754810237.16196.2169
10240.98197.155110248.64198.049710252.47 199.20910286.94212.190410309.81222.3104
#Mann= 3 , 0 , 0
 9670.84    0.12       0 9670.84    0.12       010309.81    0.12       0
#XS Ineff= 2 , 0
       0                               0
Bank Sta=9670.84,10309.81
Exp/Cntr=0.3,0.1

Type RM Length L Ch R = 1 , 6330.92,194.820400,194.820400,194.820400
XS GIS Cut Line= 6
 1283936.0449121628958.8108108041283990.77718255628834.527994633
1284034.55748114 628711.802664251284053.55717972628637.145531476
1284084.44260085628473.5754644131284132.43348086628350.207553282
#Sta/Elev= 30
9606.786 204.7269617.034202.45669628.634198.30889638.715 195.7389653.168190.0767
 9659.95188.19099671.168187.22219696.114186.57129706.805185.60739713.932183.9609
 9721.06 181.2959735.109178.13349766.992171.82899788.034166.80759829.935159.0641
9840.295157.7775 9867.92156.07599895.102155.80769912.029155.05189942.497156.6703
10018.96 156.28410052.23160.210510089.25163.357210147.45173.398410164.89178.6586
10178.95182.014210203.57 190.35510217.91 196.36610235.91202.587310249.11207.7653
#Mann= 3 , 0 , 0
9606.786    0.12       09606.786    0.12       010249.11    0.12       0
#XS Ineff= 2 , 0
       0                               0
Bank Sta=9606.786,10249.11
Exp/Cntr=0.3,0.1

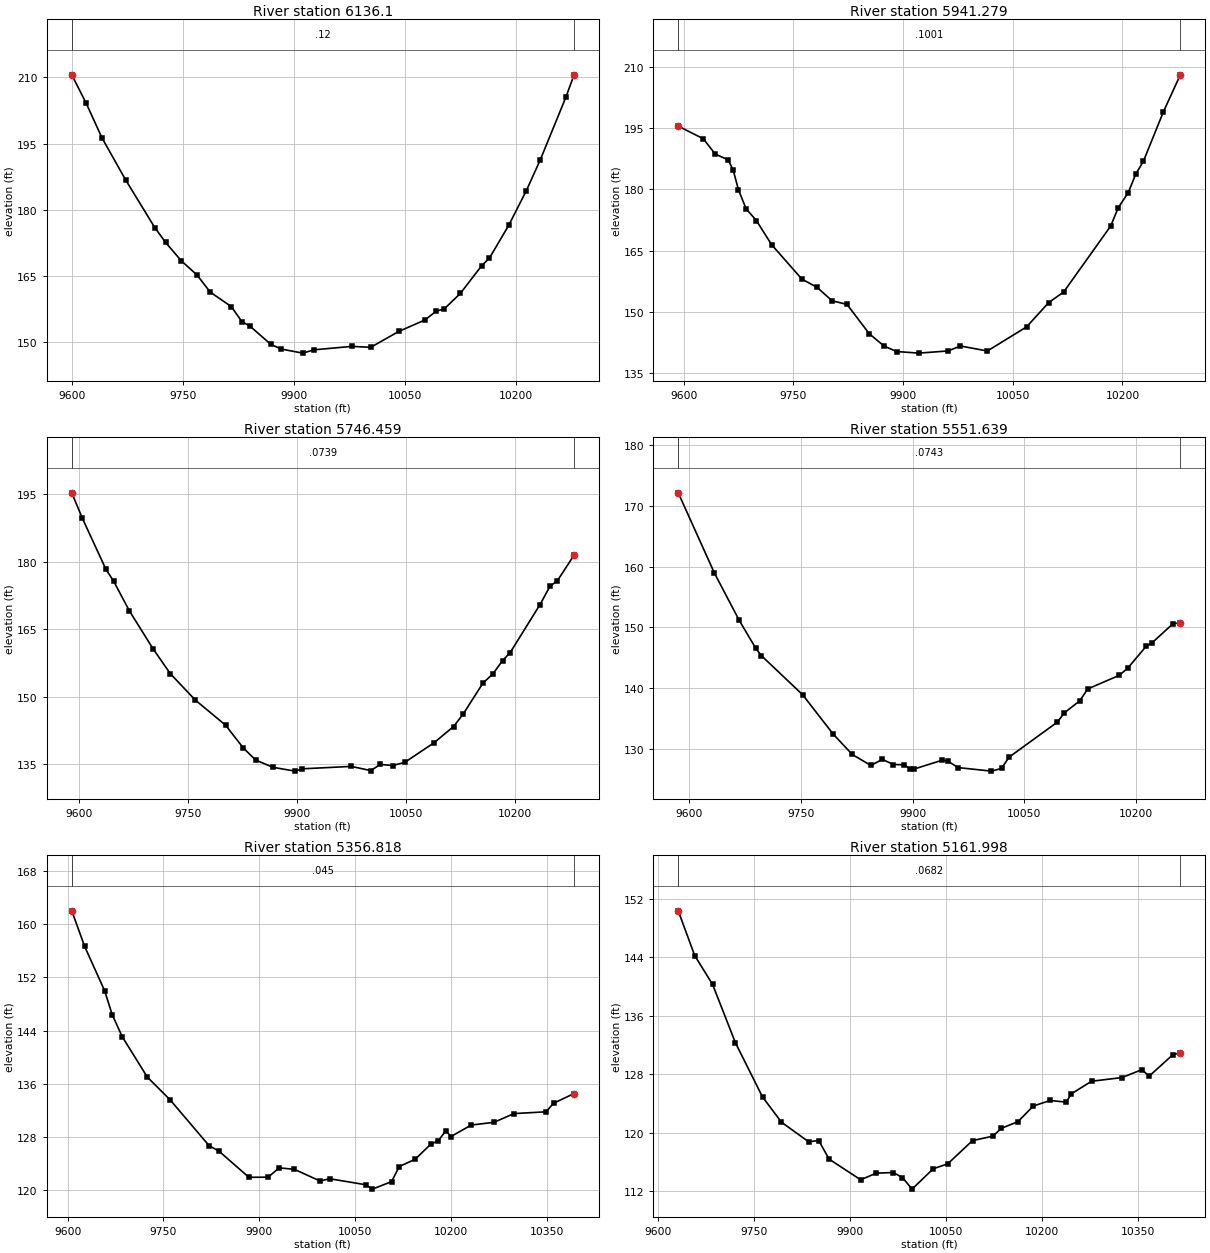
Type RM Length L Ch R = 1 ,  6136.1,194.820400,194.820400,194.820400
XS GIS Cut Line= 6
1284072.99196413 629033.108589471284187.52305767628762.187137678
1284240.80084029628654.6656426041284271.69465551628596.276660234
1284292.22556132628552.6558718681284349.82187429628414.554907233
#Sta/Elev= 30
9599.771210.60029619.298 204.125 9640.67196.24389672.727186.68329711.909175.8953
 9726.57172.52179747.528168.3903  9768.9165.1428 9786.71161.25749815.205157.9697
9829.453154.54999840.139153.56769868.635149.37749882.883148.30979911.896147.3952
9926.567148.13929977.913 148.929 10003.5148.714610041.27152.314310076.35154.8968
10092.06156.929410102.94157.4563 10124.7160.9849 10153.2167.220510163.87168.9959
10189.77176.394710213.63184.285610232.39191.255610266.96205.483910277.81  210.47
#Mann= 3 , 0 , 0
9599.771    0.12       09599.771    0.12       010277.81    0.12       0
#XS Ineff= 2 , 0
       0                               0
Bank Sta=9599.771,10277.81
Exp/Cntr=0.3,0.1

Type RM Length L Ch R = 1 ,5941.279,194.820500,194.820500,194.820500
XS GIS Cut Line= 6
1284303.51904246629111.4426517931284342.48178381629011.260945618
 1284372.0624516628921.3344060031284397.52707762628825.543046281
 1284457.1960493628555.7964674831284489.27641875628451.756816134
#Sta/Elev= 30
9592.688195.4523 9626.94192.36349643.233188.62089660.834 187.2129667.874184.6793
9674.915179.92749685.475175.22099699.556172.34289720.291166.46249761.736158.0169
9782.459155.99979803.039152.70649823.407 151.835 9853.96144.62529874.329141.6069
9891.303140.29569921.502139.90099961.722140.43799978.481141.645610015.34140.4271
10068.95146.318110099.27152.285210119.56154.835810183.99171.004510194.28175.4874
   10208  179.1810218.29183.739510228.58186.808610256.03198.954810279.16208.0067
#Mann= 3 , 0 , 0
9592.688  0.1001       09592.688  0.1001       010279.16  0.1001       0
#XS Ineff= 2 , 0
       0                               0
Bank Sta=9592.688,10279.16
Exp/Cntr=0.3,0.1

Type RM Length L Ch R = 1 ,5746.459,194.820400,194.820400,194.820400
XS GIS Cut Line= 6
1284485.77200142629149.9900535491284538.23326397629024.248859257
1284571.26737031 628926.339429961284594.02334476 628838.95572722
1284649.74625379 628580.911060811284677.61163104628488.208269015
#Sta/Elev= 30
9590.133195.32039604.825189.61729637.016178.34879647.747175.67179669.206 169.126
9701.731 160.7049725.629155.12169760.268149.21219801.819143.64429826.057138.6024
9843.085135.91169866.816134.29229897.329133.43929907.499133.95239974.628134.4902
10001.42133.5687 10014.8134.932610031.53134.673610048.25135.3927 10088.4139.7322
 10115.4143.3513 10128.9146.192410155.89153.031310169.39155.045510182.89158.0361
10193.15159.772710234.26170.448510247.96174.530210258.24175.773310280.87181.3943
#Mann= 3 , 0 , 0
9590.133  0.0739       09590.133  0.0739       010280.87  0.0739       0
#XS Ineff= 2 , 0
       09844.299        10057.22       0
Bank Sta=9590.133,10280.87
Exp/Cntr=0.3,0.1

Type RM Length L Ch R = 1 ,5551.639,194.820400,194.820400,194.820400
XS GIS Cut Line= 6
1284619.10586149629169.5935805141284779.71466541628860.109578848
1284793.96372029628825.3454213891284809.87582141628764.508710817
1284833.99199158 628700.16229485  1284897.137229628556.873584434
#Sta/Elev= 30
9585.083172.10879633.622158.95389667.012 151.1679689.273146.57559696.693145.3872
9752.345138.93519793.156132.50679818.908129.14829843.856127.35019859.343128.3437
9874.047127.5057 9888.75127.46539896.102126.79849902.053 126.7659939.985128.2245
9947.077128.06229961.259 126.99610005.78126.417810019.35126.861610029.53128.7121
 10094.5134.474410103.73135.993810124.43137.947810135.17139.911410177.47142.1401
10188.88143.321110213.94 146.953 10221.1147.432710249.85150.633510259.54150.7674
#Mann= 3 , 0 , 0
9585.083  0.0743       09585.083  0.0743       010259.54  0.0743       0
#XS Ineff= 2 , 0
       09856.105         10043.3       0
Bank Sta=9585.083,10259.54
Exp/Cntr=0.3,0.1

Type RM Length L Ch R = 1 ,5356.818,194.820400,194.820400,194.820400
XS GIS Cut Line= 6
1284707.72620434629235.3713167311284850.53448325629027.147742093
1284906.25319847628961.7158590261284987.65316692628880.159396574
1285044.80345273628808.2180532071285175.31570703628607.421948493
#Sta/Elev= 30
9606.564161.97759626.689156.63549657.963149.97879669.825146.37879685.511143.0788
9724.726137.01729760.331133.60849821.232126.73199837.153 125.8719883.545121.9753
9913.709 121.9959930.946123.39369954.625123.17239995.109121.410110009.77121.7608
10066.78120.850810076.82120.200210106.68121.324610118.78123.592810143.73124.6901
10167.85 126.93310179.76127.468910191.67128.9716 10199.6128.097810231.36129.8195
10267.08130.234710298.03131.538410348.23131.809110359.96133.084410391.78134.5346
#Mann= 3 , 0 , 0
9606.564   0.045       09606.564   0.045       010391.78   0.045       0
#XS Ineff= 2 , 0
       09925.496        10071.42       0
Bank Sta=9606.564,10391.78
Exp/Cntr=0.3,0.1

Type RM Length L Ch R = 1 ,5161.998,194.820500,194.820500,194.820500
XS GIS Cut Line= 6
1284889.14338377629314.1732383521285065.01819909629095.175116584
1285089.41639158  629056.12932461285142.86847562628955.529385358
1285286.52669784 628742.625688971285332.68855438628668.693966106
#Sta/Elev= 30
9631.527150.32189657.328144.20099685.248140.26519720.904132.31099763.287124.9036
9792.956121.45729835.339118.78679851.143  118.959867.386116.41549916.641113.5981
9941.066 114.4939967.669114.58669982.025113.90269997.089 112.31710030.19115.0978
 10052.9115.775410091.58118.943910123.24119.546210136.67120.614510162.82121.5425
10186.57123.665410212.92124.421510238.02   124.210245.94125.3202 10277.6127.0478
10325.09127.549910356.22128.623810367.87127.754110404.23130.631710416.44130.9606
#Mann= 3 , 0 , 0
9631.527  0.0682       09631.527  0.0682       010416.44  0.0682       0
#XS Ineff= 2 , 0
       09947.638        10048.89       0
Bank Sta=9631.527,10416.44
Exp/Cntr=0.3,0.1

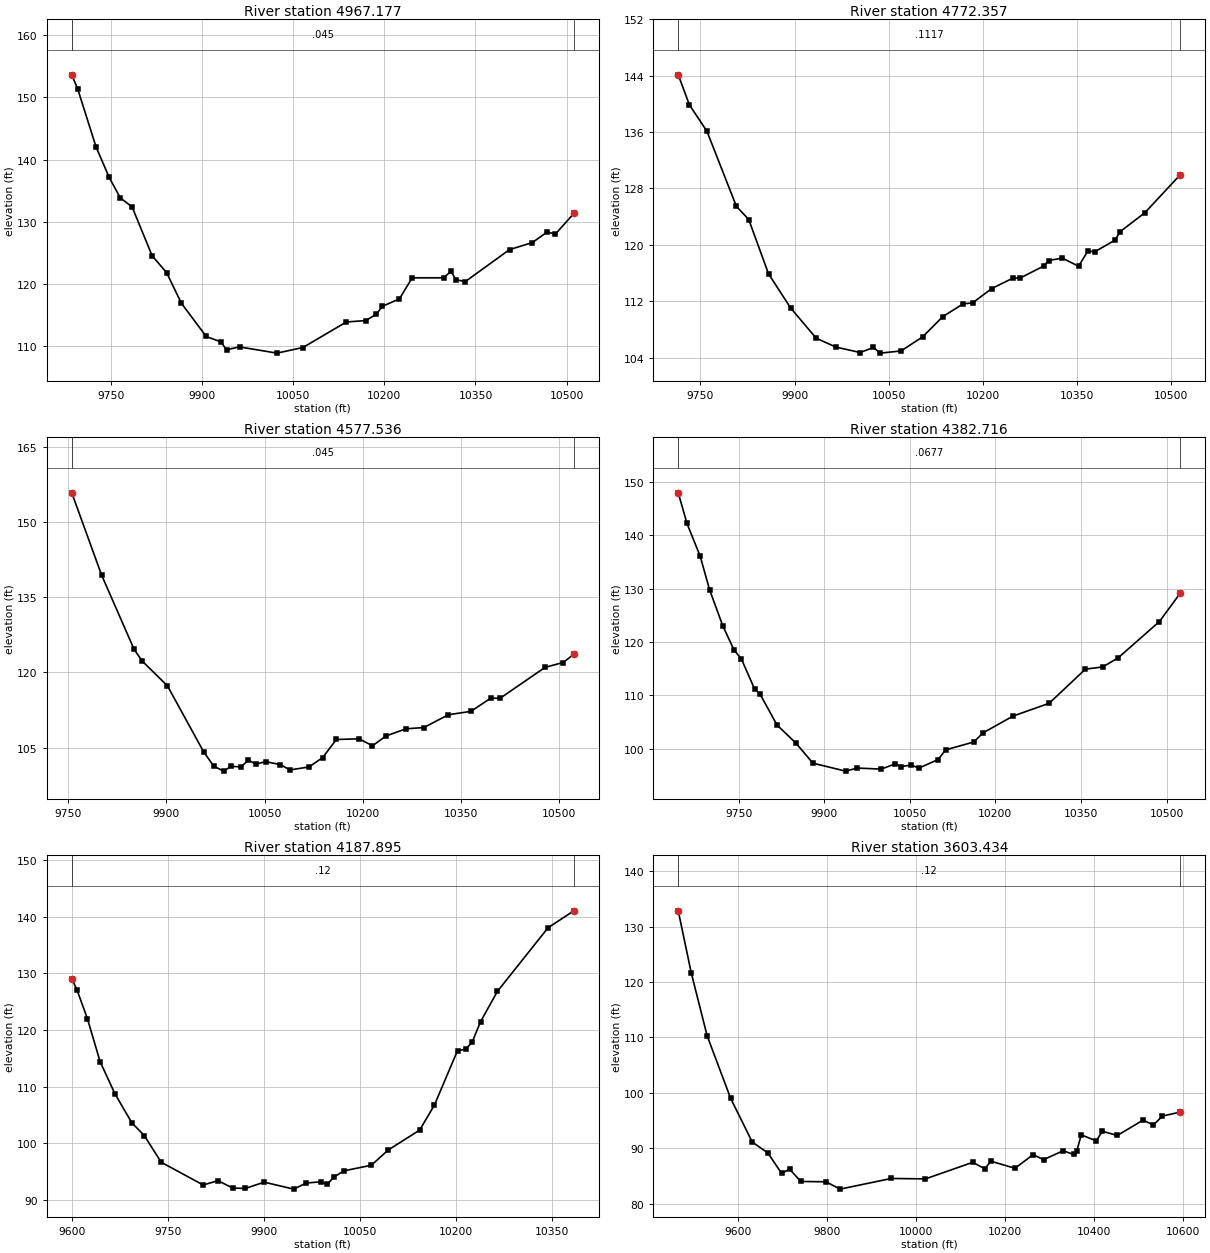
Type RM Length L Ch R = 1 ,4967.177,194.820400,194.820400,194.820400
XS GIS Cut Line= 6
1284989.21798685629377.1170957391285133.18126664629225.673918739
1285276.25985095629143.2067112921285355.08004308 629068.25394699
1285444.13076487628949.4549314681285541.04699719628781.212665066
#Sta/Elev= 30
9685.299153.63899695.103151.36169725.251142.05149746.964137.14469765.155133.8678
9784.632132.40969817.615124.56059841.437121.84779865.765116.93299906.686111.5849
9930.723110.72179940.135109.45519961.533 109.91110023.15108.911410065.82109.8102
10137.31113.909410169.23114.1468 10186.9115.154410196.77116.442510224.82117.6307
10245.75121.014810297.73121.015110309.73122.073310317.72120.726710333.09120.3992
10406.09125.547810443.65126.678610468.01128.374610481.73128.0479   10512131.3659
#Mann= 3 , 0 , 0
9685.299   0.045       09685.299   0.045       0   10512   0.045       0
#XS Ineff= 2 , 0
       09939.417         10107.7       0
Bank Sta=9685.299,10512
Exp/Cntr=0.3,0.1

Type RM Length L Ch R = 1 ,4772.357,194.820400,194.820400,194.820400
XS GIS Cut Line= 6
1285225.70068854 629525.383746521285348.89088061 629336.94881691
1285365.42364043629304.4768126761285392.16862231629235.764613837
1285517.35511136629018.7090970581285610.87354577628826.159600124
#Sta/Elev= 30
9714.559144.12329732.394139.84729760.226136.13419807.234125.46019826.928123.5894
 9858.44115.88399893.727 111.0319934.448106.74549965.821 105.48510004.48104.7135
10025.59105.431810036.45104.626310069.63104.935110104.09106.936110136.03109.7957
10168.42 111.61210183.71111.7584 10214.3113.797110248.34115.288210259.62115.2908
10297.21116.996910304.65117.770610326.73118.113310352.49116.954910367.21119.0823
10378.85119.041710411.12120.680410418.37121.841510458.21124.549410514.71129.9544
#Mann= 3 , 0 , 0
9714.559  0.1117       09714.559  0.1117       010514.71  0.1117       0
#XS Ineff= 2 , 0
       0                10112.77       0
Bank Sta=9714.559,10514.71
Exp/Cntr=0.3,0.1

Type RM Length L Ch R = 1 ,4577.536,194.820400,194.820400,194.820400
XS GIS Cut Line= 6
1285408.87395242629619.6640660021285466.62909538629496.036919013
1285551.44801244629343.6644494531285573.24157754629298.287172064
1285597.06674895629231.9920048121285693.03509733 628910.86960268
#Sta/Elev= 30
9755.401 155.9099800.912 139.483 9850.51 124.6539862.923122.28399901.438117.3427
9956.661104.1778 9972.28101.26769987.373100.27899998.693101.232310013.82101.1312
10025.17102.461910036.53101.692810051.66102.173910074.05101.582910088.61100.5206
10117.68101.1071 10138.6 102.98710159.52106.601210194.23106.740810214.71105.3438
10235.19 107.30410265.91108.738410293.22108.992510330.77111.557510364.91 112.221
10395.63114.888810409.32114.816710478.22121.015910505.79121.992510522.24123.6261
#Mann= 3 , 0 , 0
9755.401   0.045       09755.401   0.045       010522.24   0.045       0
#XS Ineff= 2 , 0
       0                               0
Bank Sta=9755.401,10522.24
Exp/Cntr=0.3,0.1

Type RM Length L Ch R = 1 ,4382.716,194.820500,194.820500,194.820500
XS GIS Cut Line= 6
1285736.80130768629758.6103202251285740.19156659  629539.0782426
1285676.75605741629325.3058386151285669.73686993629226.443216518
1285686.56974581629092.4258918321285736.67134163628896.913712651
#Sta/Elev= 30
9644.011147.93299659.329142.20149682.477136.06149698.928129.79279721.961123.0563
9741.688118.52529754.811116.78899777.777111.19949787.619 110.1949817.214104.4323
9850.165101.06859880.05797.297069937.30695.800639957.904 96.37439999.93496.17938
10024.5797.1704810035.1196.6457610052.3196.94287 10065.996.3656110099.5597.97301
10112.7899.7819910162.22101.259910178.62102.987710231.27106.127110294.25108.5061
 10357.8114.903610388.07 115.31410414.98116.998910487.53123.820110524.19129.1509
#Mann= 3 , 0 , 0
9644.011  0.0677       09644.011  0.0677       010524.19  0.0677       0
#XS Ineff= 2 , 0
       0 9842.74                       0
Bank Sta=9644.011,10524.19
Exp/Cntr=0.3,0.1

Type RM Length L Ch R = 1 ,4187.895,584.461200,584.461200,584.461200
XS GIS Cut Line= 6
1285886.88909477629751.3712520751285898.31789598629625.455163583
1285886.90175059 629380.84358336 1285882.1877571629167.553512588
1285884.74918669629084.3747641741285898.78782719 628968.75633876
#Sta/Elev= 30
9599.866129.0273 9607.83127.13119624.358121.97959644.192114.37679667.332108.7136
9693.625103.60459713.336101.30439739.60196.619089805.24892.592899828.26693.36148
9851.28492.054159871.01491.987679900.60893.094579946.60591.862799966.30692.94281
9989.27793.158219999.12192.6838110008.9793.9639510025.3895.1007510068.0496.08557
 10094.398.7728510143.52102.3014 10166.5106.7165 10202.6116.339810215.73116.5978
10225.58117.880610238.71121.480510264.96126.815410344.17138.0727 10384.4141.0538
#Mann= 3 , 0 , 0
9599.866    0.12       09599.866    0.12       0 10384.4    0.12       0
#XS Ineff= 2 , 0
       09830.902        10060.29       0
Bank Sta=9599.866,10384.4
Exp/Cntr=0.3,0.1

Type RM Length L Ch R = 1 ,3603.434,127.213400,127.213400,127.213400
XS GIS Cut Line= 6
1285931.00665602629792.4401622411286126.83998936629616.745717794
1286297.03553858 629507.18689549 1286423.1430788 629413.38454622
1286452.72540599629338.5165511371286555.58998933628927.058217779
#Sta/Elev= 30
9465.928132.87529495.046121.70799530.832110.31659583.72498.998769632.20891.12771
 9667.4789.144079698.32485.439849715.95586.248879741.29184.00334 9797.8883.94023
 9829.64  82.6179944.47984.5418810021.4884.4669310127.6987.4561910154.8986.28685
10168.4987.6599310222.6186.3803810263.1988.8424710286.8687.9403510330.8389.54837
 10354.588.8779210361.2689.4239510371.4192.4248110405.2391.3274510418.7593.07171
10452.5792.3067510510.0695.0663610533.7494.2170310554.0395.8187610594.0796.53261
#Mann= 3 , 0 , 0
9465.928    0.12       09465.928    0.12       010594.07    0.12       0
#XS Ineff= 2 , 0
       0 9960.94        10088.35       0
Bank Sta=9465.928,10594.07
Exp/Cntr=0.3,0.1