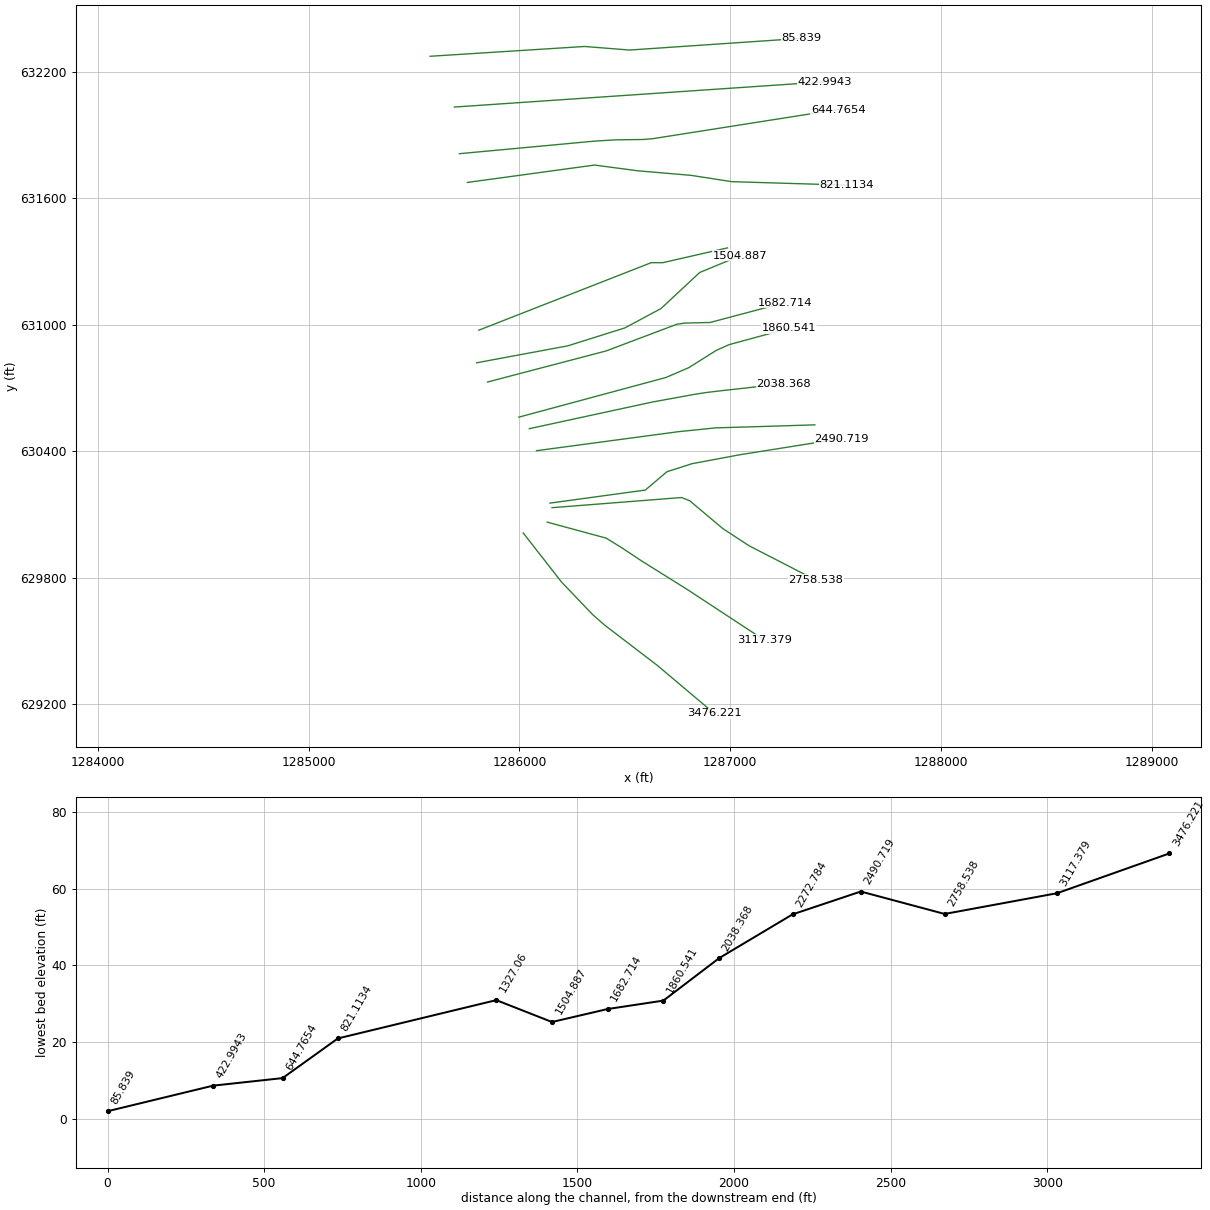
HEC-RAS study 770_ras.prj: 770

--- 770_ras.g01 (geometry) --- (continued)

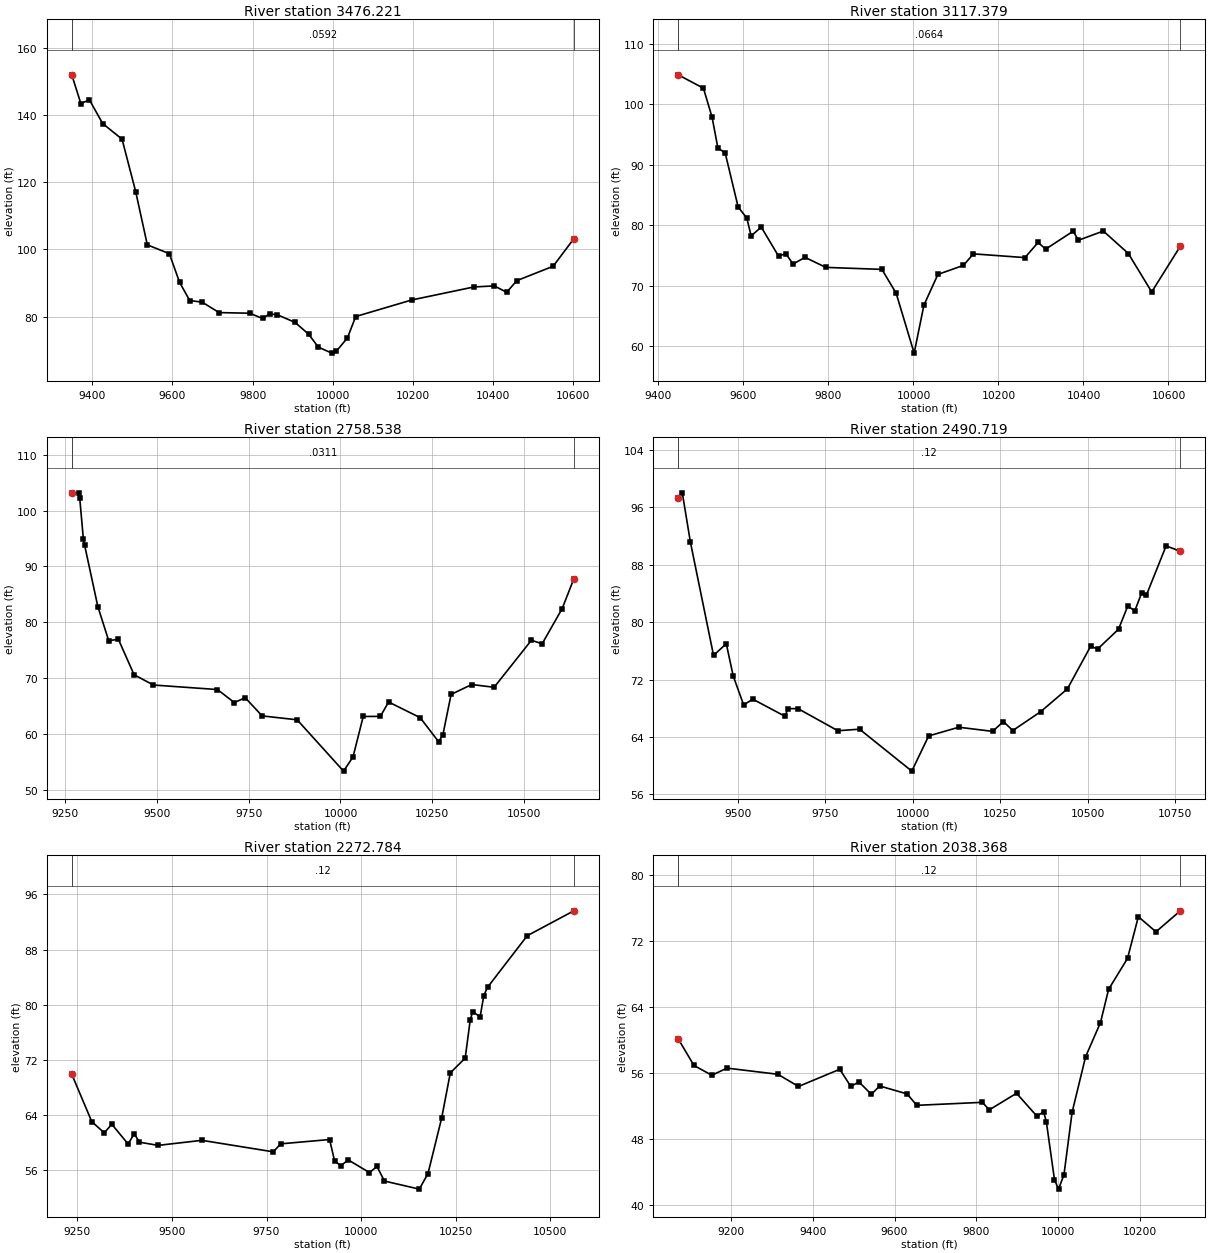
Type RM Length L Ch R = 1 ,3476.221,358.841500,358.841500,358.841500
XS GIS Cut Line= 6
1286018.08606083630011.4276871621286199.81096634629778.646590107
1286347.79672056 629623.828070941286404.25261212629574.341861641
1286654.50616573629382.9377757141286924.08297697629155.628649271
#Sta/Elev= 30
9348.903151.89679371.543143.36259392.937144.45919425.939137.42569474.372132.7605
9508.444117.11839537.377101.35659592.34298.73277 9617.7190.253869643.17784.79781
9673.99684.33283 9716.5981.220539792.32281.034279824.68779.489579842.35880.81157
9861.49680.59207 9905.9578.300149939.576  74.8249963.95370.967539997.51169.17266
10008.4969.6739210036.6273.7039910057.1380.0515710196.4184.9560910351.7488.83634
10403.0289.1609210433.7387.2513210458.9990.7173510549.7194.9982210601.33103.1816
#Mann= 3 , 0 , 0
9348.903  0.0592       09348.903  0.0592       010601.33  0.0592       0
#XS Ineff= 2 , 0
       09924.087        10051.54       0
Bank Sta=9348.903,10601.33
Exp/Cntr=0.3,0.1

Type RM Length L Ch R = 1 ,3117.379,358.841600,358.841600,358.841600
XS GIS Cut Line= 6
1286132.01577058630062.8828705551286411.96368724 629986.92800945
1286490.99785781629937.7645660791286577.58512017629880.130187422
1286795.92840835 629743.660849721287160.89966264629503.995006859
#Sta/Elev= 30
9446.577104.88639505.922102.66449526.31997.826659539.91792.750489556.91491.98536
9587.50983.003479607.90681.177199618.10478.21637  9641.979.677059682.69374.85488
9699.69175.290229716.68873.555259744.87274.665579793.833 73.00319925.77372.67475
9959.32768.7192810001.6258.8085910024.6466.7546910057.5271.8420410117.6473.33504
   1014175.2456610262.2774.62254 10293.277.1282410311.1376.0294910376.09 79.0073
10387.8677.4866210446.7479.0209310505.61 75.300310560.5668.9378910627.8776.50878
#Mann= 3 , 0 , 0
9446.577  0.0664       09446.577  0.0664       010627.87  0.0664       0
#XS Ineff= 2 , 0
       09913.491         10119.9       0
Bank Sta=9446.577,10627.87
Exp/Cntr=0.3,0.1

Type RM Length L Ch R = 1 ,2758.538,267.818600,267.818600,267.818600
XS GIS Cut Line= 6
1286154.54832268630131.4853011221286769.13165599630179.662384465
1286808.19415602630164.0373844651286964.73670593 630032.43982774
1287089.38397089 629950.892409281287405.48703644629788.164733693
#Sta/Elev= 30
9268.012103.15989286.406103.12629289.697102.2099 9299.5794.922559302.86193.84211
9339.06182.816059368.67976.722399395.00676.980059437.78870.636739490.44268.80002
 9664.8667.992029710.93265.66411 9740.5566.530559786.62363.282869882.05962.58043
10008.4453.4072210034.2855.9543610062.0163.1769810108.7863.19614 10131.265.76399
10217.1662.96816 10267.358.6728410278.8759.8351310301.42 67.121610357.7168.88979
10418.6368.3958310520.2676.8047710549.4276.1663510604.1282.4752110635.8487.79865
#Mann= 3 , 0 , 0
9268.012  0.0311       09268.012  0.0311       010635.84  0.0311       0
#XS Ineff= 2 , 0
       09895.589        10111.99       0
Bank Sta=9268.012,10635.84
Exp/Cntr=0.3,0.1

Type RM Length L Ch R = 1 ,2490.719,217.934900,217.934900,217.934900
XS GIS Cut Line= 6
1286144.99299851630153.2372545451286597.46695685630215.086212873
1286699.46348462630301.8917684261286817.88744304630339.963310391
1287043.58188751630382.2810187191287528.60792914630459.320949286
#Sta/Elev= 30
9328.778 97.32299340.374 97.98499363.553 91.1309 9429.7875.358379466.20576.98787
9486.07372.488389515.87568.474369542.36669.256569635.083 66.86199641.70667.95189
9671.50867.948449785.459 64.87249847.47265.09015 9996.9359.2512410045.1264.14845
10131.3165.3620910228.0364.7849310258.8966.1458110285.9464.9029310365.6667.52805
10442.0770.7044210508.5176.6318310528.4476.2388610588.2379.0005310614.8182.23898
10634.74 81.552110654.6784.0777510667.9683.7386410724.43 90.601210765.0489.84876
#Mann= 3 , 0 , 0
9328.778    0.12       09328.778    0.12       010765.04    0.12       0
#XS Ineff= 2 , 0
       09953.253        10271.55       0
Bank Sta=9328.778,10765.04
Exp/Cntr=0.3,0.1

Type RM Length L Ch R = 1 ,2272.784,234.416800,234.416800,234.416800
XS GIS Cut Line= 6
1286081.12529027630401.8122687041286752.78327635  630491.8730326
1286933.66638997630510.3929084091286935.66371998630510.289598182
 1287085.8995958630514.6594909431287401.65480414630524.425115928
#Sta/Elev= 30
9235.01569.937529287.87463.080259320.97661.442499340.83762.69885 9383.8759.83721
9400.42161.322389413.66260.098619463.31559.633419579.17160.364189767.85358.69752
9787.714 59.85749916.79660.479799929.98857.383819946.478 56.70219966.26657.52037
10022.3355.6925610042.1256.5757710061.9154.4652610153.9753.2962710176.9455.53957
10213.0563.5641210236.0270.1309410275.4172.2749210288.5477.7360810295.1179.02092
 10314.878.2434810324.6581.3382910334.4982.5323910439.5390.0057210562.7293.60737
#Mann= 3 , 0 , 0
9235.015    0.12       09235.015    0.12       010562.72    0.12       0
#XS Ineff= 2 , 0
       09910.243        10199.07       0
Bank Sta=9235.015,10562.72
Exp/Cntr=0.3,0.1

Type RM Length L Ch R = 1 ,2038.368,177.826800,177.826800,177.826800
XS GIS Cut Line= 6
 1286046.8016502630506.3073497271286630.25911874 630632.61583361
1286829.66732344 630669.006607191286884.38798097630677.599770963
1286955.66541934630686.1494789121287252.33413512630719.046580181
#Sta/Elev= 30
9072.14660.102739110.51756.881019154.15655.695069191.08156.560429315.28355.81317
9365.63654.336849466.34156.421589493.195 54.34949513.33654.879499543.54853.37779
9563.68954.397159630.82553.431679654.32352.05009  9814.552.413769831.17551.49981
9897.76753.51231 9947.4850.736519964.002 51.2619 9970.6150.031959990.43643.02042
10000.34 41.894610013.5443.6340310033.3551.1922710066.36 57.944510102.6762.08344
10122.4866.1102710168.6969.86062 10195.174.9129610238.0273.0815810297.4975.62223
#Mann= 3 , 0 , 0
9072.146    0.12       09072.146    0.12       010297.49    0.12       0
#XS Ineff= 2 , 0
       0 9883.35        10083.46       0
Bank Sta=9072.146,10297.49
Exp/Cntr=0.3,0.1

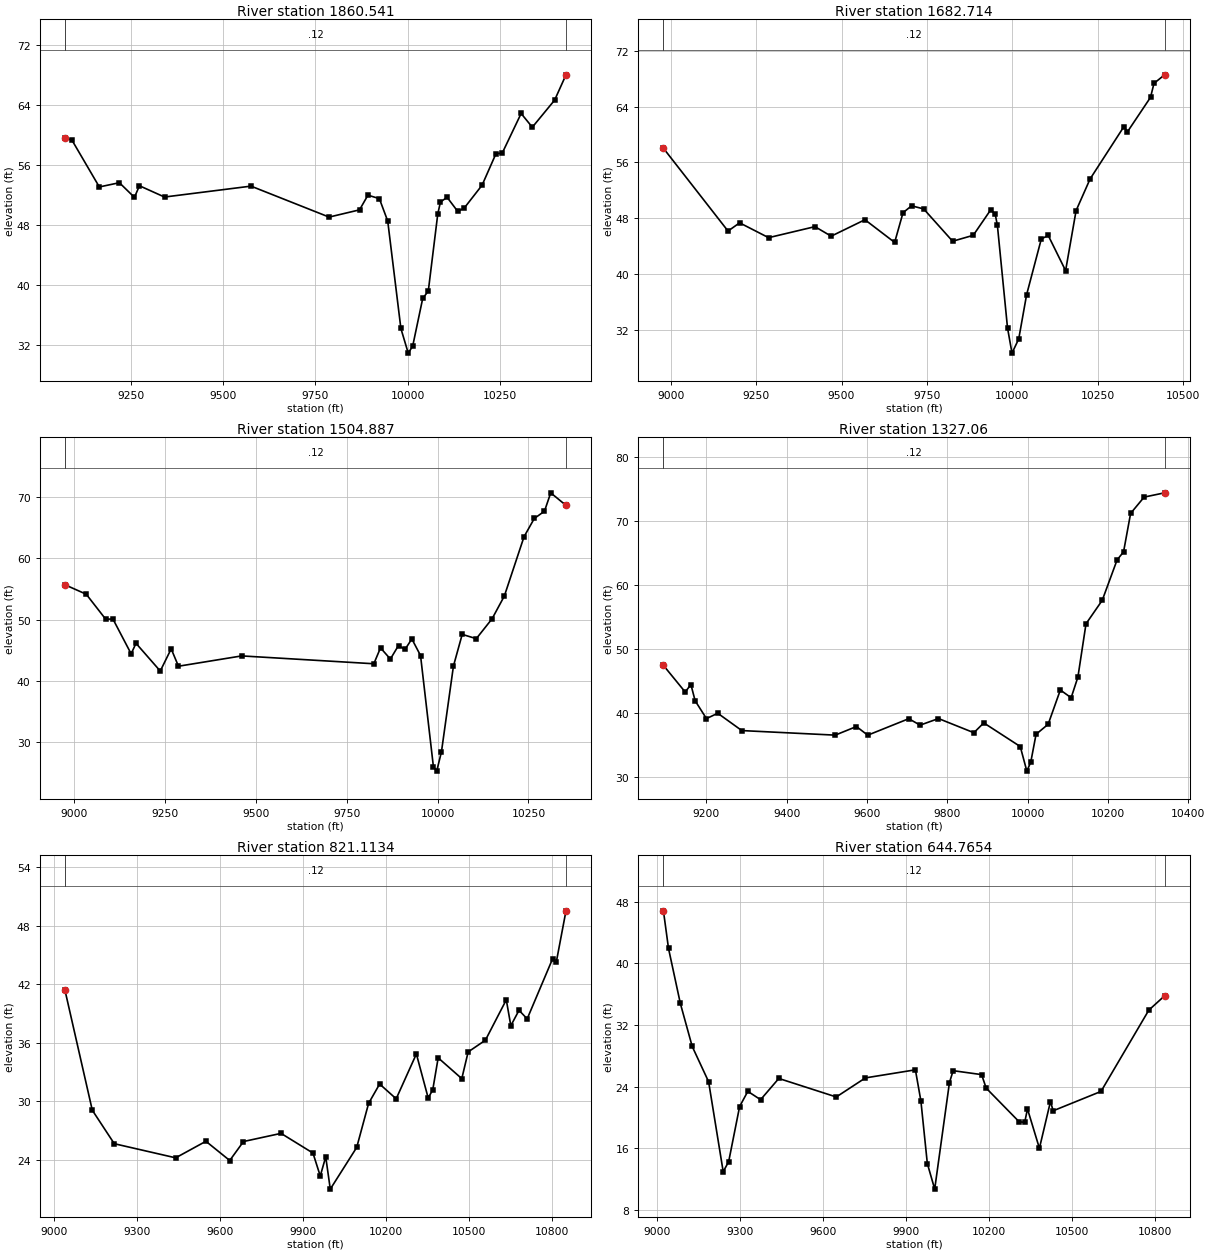
Type RM Length L Ch R = 1 ,1860.541,177.826700,177.826700,177.826700
XS GIS Cut Line= 6
1285997.32248357630560.9948497271286695.02572802 630749.10139212
1286803.29536504 630795.673486681286933.37853348630877.419476435
1286995.45589244630905.1794065091287278.98352656630982.339208856
#Sta/Elev= 30
9071.533 59.58839090.23459.342069164.87853.046279219.16553.61171 9259.8851.65273
9273.45253.20505 9341.3151.698719575.42253.155329786.84449.020389869.21249.98625
9891.96451.947819922.90151.484689945.52648.490819981.16834.1392210001.0530.84875
10013.0931.78148 10040.238.1472910055.34 39.138110081.0449.4477910088.2251.02988
10106.1951.6681210134.9149.7887610152.2950.2047610200.9553.28163 10238.557.48872
10255.5457.5709510306.6562.8585110336.9261.0242310397.39 64.6493 10428.168.02234
#Mann= 3 , 0 , 0
9071.533    0.12       09071.533    0.12       0 10428.1    0.12       0
#XS Ineff= 2 , 0
       09914.167        10118.58       0
Bank Sta=9071.533,10428.1
Exp/Cntr=0.3,0.1

Type RM Length L Ch R = 1 ,1682.714,177.826800,177.826800,177.826800
XS GIS Cut Line= 6
1285848.88498354630727.6615163981286411.53637156630875.153349638
1286747.59599659631001.960381076 1286785.6201441631007.317092031
1286904.47946319631010.0998569581287259.41588604631104.238035232
#Sta/Elev= 30
8978.99458.039239168.01546.163419201.91747.343559286.67145.214949422.27846.79571
9469.74345.429069568.51147.786599655.37944.534639679.92248.796719704.97849.78417
9740.29149.337179825.01444.703479885.33145.553059936.10449.184939949.35748.64242
9955.98346.964249985.55332.283289998.68528.6590910018.3830.6981310041.4137.03342
10084.4545.0342210104.6745.5300510155.4840.4869610186.1949.0972510227.1453.63508
 10326.161.1418410336.3460.3888910403.91 65.338310414.0367.3411110444.9868.56552
#Mann= 3 , 0 , 0
8978.994    0.12       08978.994    0.12       010444.98    0.12       0
#XS Ineff= 2 , 0
       09931.525        10089.59       0
Bank Sta=8978.994,10444.98
Exp/Cntr=0.3,0.1

Type RM Length L Ch R = 1 ,1504.887,177.826800,177.826800,177.826800
XS GIS Cut Line= 6
1285796.80165023630818.8073497271286229.51949784630899.300887302
1286500.34312886630984.3504381921286671.63213921631076.216442212
1286855.23753044631247.3487568351287046.27910608631326.057248592
#Sta/Elev= 30
8974.84355.696599033.69554.144949087.10350.075519107.13150.096649157.20144.42169
9170.55346.136369237.31441.610959267.35645.233419287.38442.396969461.34544.07946
9824.79242.798119843.14945.394639870.29343.567319892.66245.775369910.42845.12778
9929.38246.849179953.27144.139949988.64926.010749997.75525.2776910010.8428.44108
10043.79 42.4255 10067.947.59493 10106.646.8899310150.0550.1372610183.7853.84646
   1023863.5298910266.2266.5087910294.1867.6905310311.4270.69182 10353.468.64106
#Mann= 3 , 0 , 0
8974.843    0.12       08974.843    0.12       0 10353.4    0.12       0
#XS Ineff= 2 , 0
       09930.839         10079.1       0
Bank Sta=8974.843,10353.4
Exp/Cntr=0.3,0.1

Type RM Length L Ch R = 1 , 1327.06,505.947000,505.947000,505.947000
XS GIS Cut Line= 4
1285807.35555637630973.549754545 1286625.1530681631293.843518704
1286680.01417917631293.8435187041286986.95862359  631363.9824076
#Sta/Elev= 30
9093.075 47.45689147.38643.297459161.47944.47498 9172.0541.942119200.23839.16049
9228.42639.992069288.32537.293049520.87536.582199573.728 37.92269601.91636.57519
9704.09739.144589732.28538.13899 9778.0939.167439866.17736.959479890.84238.49109
9981.68834.806359998.09230.9722910007.9332.3851110021.0636.7163210051.2138.27915
 10081.543.6164810108.4342.4122310125.2545.6278310145.4453.9373510185.8357.59269
10222.8563.8923310238.9565.15491 10256.571.1400510290.1673.6845410341.07 74.3512
#Mann= 3 , 0 , 0
9093.075    0.12       09093.075    0.12       010341.07    0.12       0
#XS Ineff= 2 , 0
       0 9905.94        10064.97       0
Bank Sta=9093.075,10341.07
Exp/Cntr=0.3,0.1

Type RM Length L Ch R = 1 ,821.1134,176.348000,176.348000,176.348000
XS GIS Cut Line= 6
1285753.10208413631674.5046156641286356.40069523631756.969893426
1286560.05613515631729.8822918681286815.19936436631707.985590473
1287007.22772083631678.1968173241287553.23466527631661.703761771
#Sta/Elev= 30
9040.312  41.4419139.48929.085569218.96125.651949440.82124.203739550.09525.90062
 9636.1923.930039685.84225.874799821.54126.712089936.96124.692419963.30422.33978
9983.06124.312019999.52620.9951110095.0225.2714910138.0529.7917910177.8931.77083
10237.6530.2556610310.6334.85615 10353.330.3415710369.7131.1603310389.4134.45602
10474.7532.3235310497.7235.0611510560.0936.2642810635.5840.4045610651.99  37.751
10681.5339.3303810711.0738.4532310802.9844.6167510816.1144.2495110851.3349.52872
#Mann= 3 , 0 , 0
9040.312    0.12       09040.312    0.12       010851.33    0.12       0
#XS Ineff= 2 , 0
       09927.808         10073.9       0
Bank Sta=9040.312,10851.33
Exp/Cntr=0.3,0.1

Type RM Length L Ch R = 1 ,644.7654,221.771100,221.771100,221.771100
XS GIS Cut Line= 6
1285714.93894766631810.8501738061286358.56485266631870.727604439
1286457.38011468631876.6110443821286587.12535832631878.284105231
1286633.47122465631882.2009084571287511.81394766632020.485590478
#Sta/Elev= 30
9023.99746.823319042.386 41.9415 9085.2134.786089128.03429.204729187.32924.62009
9240.03612.932219259.80114.24349 9299.3321.400139328.97823.372439375.09622.29008
9440.97925.046929648.64922.643069753.914 25.12029934.52426.169379954.36422.12903
9977.63913.9973310004.2610.6706210057.5624.5095910070.8826.0583310173.7125.54615
10190.2823.7931810309.6519.4107710329.5519.3532110339.4921.0926110382.64 15.9759
10422.5122.0384610432.4820.8497310605.2523.3639610778.0333.9255210834.8735.77661
#Mann= 3 , 0 , 0
9023.997    0.12       09023.997    0.12       010834.87    0.12       0
#XS Ineff= 2 , 0
       0 9918.45        10081.71       0
Bank Sta=9023.997,10834.87
Exp/Cntr=0.3,0.1

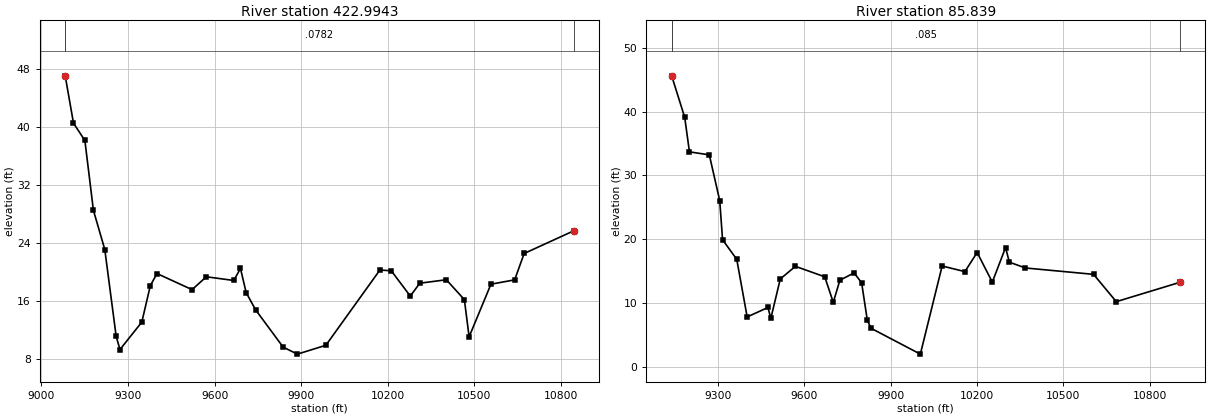
Type RM Length L Ch R = 1 ,422.9943,337.155300,337.155300,337.155300
XS GIS Cut Line= 2
1285691.50144765632032.2043404731287449.31394768632151.996007144
#Sta/Elev= 30
9082.292 47.00769110.98840.491369150.44938.111619180.04528.499119219.50623.10433
9258.96811.138939272.1219.3402289347.75513.112389377.351 18.13799400.37119.79702
9522.04317.58094 9571.3719.351359666.73418.843399689.75420.504889709.484 17.1701
9742.36914.796969837.7339.669665 9887.068.7072599985.7139.92416810173.1520.28823
10212.6220.1697510278.3816.6954810311.27 18.468410403.3518.9415710465.83 16.2061
10482.2711.08471 10557.918.3315610640.1118.92832   1067322.5571610844.1825.66496
#Mann= 3 , 0 , 0
9082.292  0.0782       09082.292  0.0782       010844.18  0.0782       0
#XS Ineff= 2 , 0
       09869.825        10076.05       0
Bank Sta=9082.292,10844.18
Exp/Cntr=0.3,0.1

Type RM Length L Ch R = 1 ,  85.839,0.000000,0.000000,0.000000
XS GIS Cut Line= 4
1285576.48408654632273.0897571441286309.25819883632319.568987265
 1286522.6646421632302.6036460251287338.63686436632358.159201577
#Sta/Elev= 30
9139.59745.59144 9184.9139.088439201.34733.695029270.38333.224469306.54526.06434
9316.40719.947049365.71816.87147 9401.88 7.864189474.2039.3463049484.0667.627062
 9516.94 13.80989569.53915.780689671.44914.146159701.03610.148929724.04813.60612
9773.359  14.7589799.65913.203289819.3837.3248629832.5336.08325310003.632.045355
10079.32 15.836510158.2514.95658   1020117.9447610253.6213.3129610299.6618.72102
10312.8116.4367410368.7115.5259910605.48 14.5293 10684.410.2547910905.7813.28538
#Mann= 3 , 0 , 0
9139.597   0.085       09139.597   0.085       010905.78   0.085       0
#XS Ineff= 2 , 0
       09875.933        10071.39       0
Bank Sta=9139.597,10905.78
Exp/Cntr=0.3,0.1